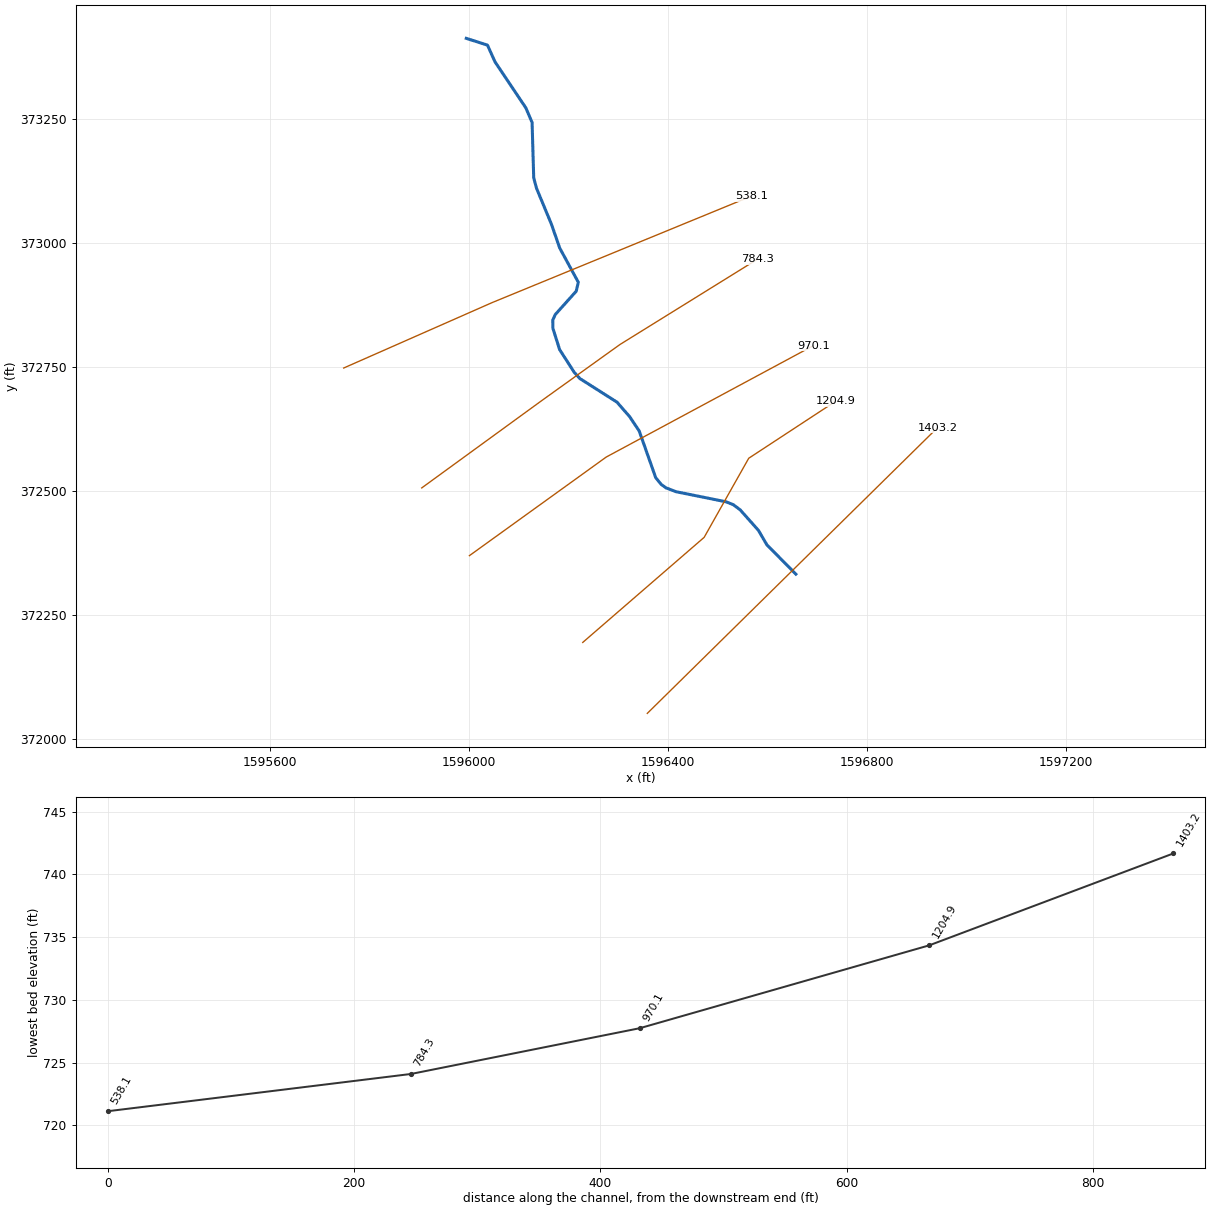
--- MAYNRDBR.prj (project) ---

Proj Title=MAYNRDBR
Current Plan=p01
Default Exp/Contr=0,0
English Units
Geom File=g01
Flow File=f01
Plan File=p01
BEGIN DESCRIPTION:
END DESCRIPTION:
DSS Export Rating Curves= 0
DSS Export Rating Curve Sorted= 0
DSS Export Volume Flow Curves= 0
DXF OffsetX= 0
DXF OffsetY= 0
DXF ScaleX= 0
DXF ScaleY= 0

--- MAYNRDBR.p01 (plan) ---

Plan Title=Floodplain
Program Version=4.00
Geom File=g01
Flow File=f01
K Sum by GR=0
Std Step Tol=0.01
Critical Tol=0.01
Num of Std Step Trials=20
Max Error Tol=0.3
Flow Tol Ratio=0.001
Split Flow NTrial=30
Split Flow Tol=0.02
Split Flow Ratio=0.02
Log Output Level=0
Friction Slope Method=1
Unsteady Friction Slope Method=2
Unsteady Bridges Friction Slope Method=1
Global Log Level=0
CheckData=False
Run HTab=0
Run UNet=0
Run PostProcess=0
UNET Theta=0
UNET Theta Warmup=0
UNET ZTol=0
UNET ZSATol=0
UNET MxIter=0
UNET MaxInSteps=0
UNET DtIC=0
UNET DtMin=0
UNET MaxCRTS=0
UNET WFStab=0
UNET SFStab=0
UNET WFX=0
UNET SFX=0
UNET DSS MLevel=0
UNET DZMax Abort=0
UNET Convert EG Bridges=0
UNET Use Existing IB Tables=0
UNET Froude Limit=0
UNET Froude Power=0
Write IC File=0
Echo Input=False
Echo Output=False
Write Detailed=0

--- MAYNRDBR.f01 (steady flow) ---

Flow Title=NFF Regression Equation
Program Version=4.00
Number of Profiles=1
Profile Names=P100yr
River Rch & RM=MAYNRDBR,Main      ,1403.2
     358
Boundary for River Rch & Prof#=MAYNRDBR,Main      ,1
Up Type=0
Dn Type=3
Dn Slope=0.019939

--- MAYNRDBR.g01 (geometry) ---

Geom Title=USGS 10m DEM
Program Version=4.00

River Reach=MAYNRDBR        ,Main
Reach XY= 30
     1596656.995      372332.796     1596598.796      372391.786
     1596581.719      372421.022     1596544.913      372462.438
     1596531.194      372472.641     1596516.785      372478.397
     1596416.414      372498.721     1596395.948      372506.516
     1596386.052      372513.796     1596375.322      372527.132
     1596342.148      372621.122     1596322.846      372650.084
     1596297.556      372679.069     1596223.067      372726.566
     1596211.555      372739.241     1596182.248      372784.948
     1596168.743       372827.81     1596168.442      372844.358
     1596173.526      372855.643     1596215.619      372902.552
     1596219.784      372920.625     1596182.397      372989.583
     1596165.729      373037.678     1596135.825      373109.766
     1596130.178      373130.846     1596126.904      373242.367
     1596114.182      373272.093      1596052.43      373364.405
     1596037.257      373398.124     1595994.623      373411.847

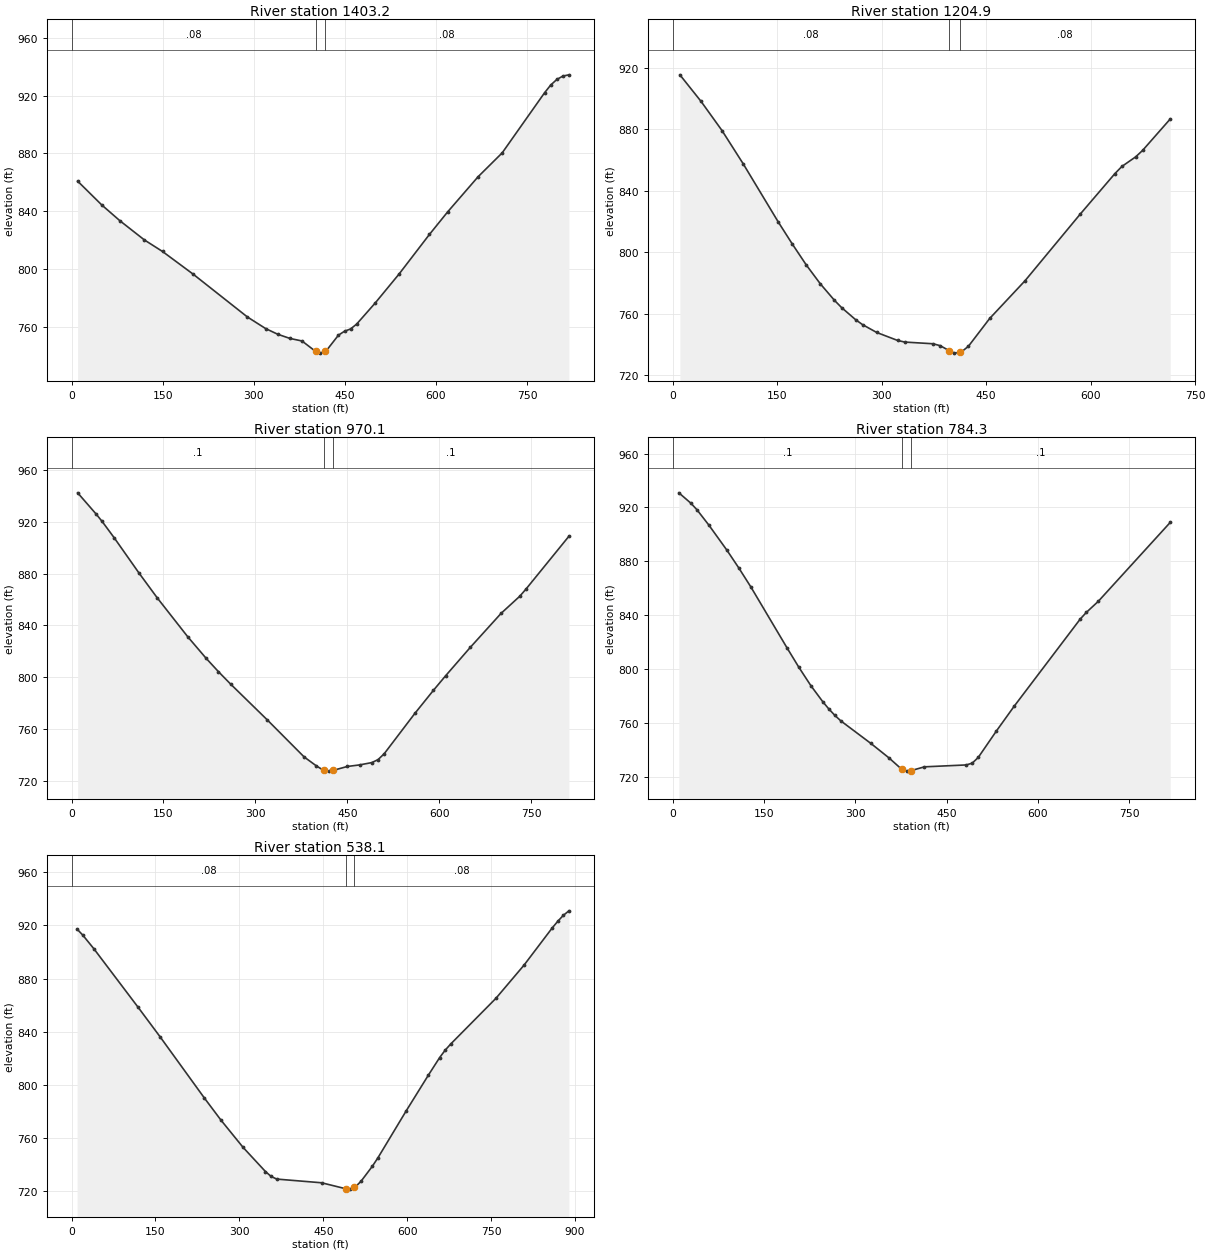
Type RM Length L Ch R = 1 ,1403.2  ,192.1,198.3,204.4
XS GIS Cut Line= 3
     1596358.461      372052.317     1596649.971      372339.914
     1596941.481      372627.512
#Sta/Elev= 30
      10  860.87    49.9  844.29    79.9  833.31   119.9  820.12   149.8  812.11
   199.8  796.54   289.6  766.72   319.6   758.7   339.6  754.74   359.6  751.87
   379.5  750.09     402  742.83   409.5  741.68     417  742.94   419.5  743.35
   439.5  754.13   449.5  756.85   459.4  758.42   469.4  761.77   499.4   776.1
   539.3  796.48   589.3  823.91   619.2  839.48   669.2  863.78   709.1  880.42
     779  922.13     789  927.42     799  931.27     809  933.63     819   934.5
#Mann= 3 , 0 , 0
       0     .08       0     402    .045       0     417     .08       0
Bank Sta=402,417
XS Rating Curve= 0 ,0
Exp/Cntr=0.3,0.1

Type RM Length L Ch R = 1 ,1204.9  ,247.4,234.8,222.2
XS GIS Cut Line= 4
     1596228.721      372195.199     1596472.685      372406.799
     1596562.304      372566.122     1596736.563      372680.636
#Sta/Elev= 30
    10.1  915.44    40.4  898.22    70.6  879.18   100.9  857.63   151.4  819.67
   171.6  805.31   191.7  791.67   211.9  779.38   232.1   768.7   242.2  764.04
   262.4  756.14   272.5  752.87   292.7  747.81   322.9  742.57   333.1  741.55
   373.7  740.44   383.9   739.2   396.7  736.02   404.2  734.35   411.7   734.9
   414.3  735.09   424.5  738.83     455   756.9   505.7  781.42   585.2   824.9
   634.8  851.15   644.8   855.8   664.6  862.05   674.5  866.21   714.3  886.71
#Mann= 3 , 0 , 0
       0     .08       0   396.7    .045       0   411.7     .08       0
Bank Sta=396.7,411.7
XS Rating Curve= 0 ,0
Exp/Cntr=0.3,0.1

Type RM Length L Ch R = 1 ,970.1   ,182.9,185.8,188.7
XS GIS Cut Line= 3
      1596000.93       372369.95      1596276.02      372568.612
     1596691.754       372792.66
#Sta/Elev= 30
      10  942.25    39.9  926.02    49.9  920.22    69.9  907.41   109.8  880.62
   139.7  861.38   189.6  831.32   219.6  814.72   239.5  804.52   259.5  794.87
   319.4  767.24   379.5   738.7   399.6  731.75   409.7  728.82   412.2  728.55
   419.7  727.75   427.2  728.37   449.9  731.32     470  732.54     490  734.33
   500.1  736.61   510.1   741.1   560.4  772.36   590.5  790.03   610.6  801.36
   650.8  823.21   701.1  849.44   731.2  862.46   741.3  867.93   811.6  908.79
#Mann= 3 , 0 , 0
       0      .1       0   412.2    .045       0   427.2      .1       0
Bank Sta=412.2,427.2
XS Rating Curve= 0 ,0
Exp/Cntr=0.3,0.1

Type RM Length L Ch R = 1 ,784.3   ,250.8,246.2,241.6
XS GIS Cut Line= 4
     1595905.096      372506.376     1596144.081      372680.636
     1596303.404      372795.149      1596579.73      372966.919
#Sta/Elev= 30
     9.9   930.8    29.6  923.11    39.4  918.35    59.2  906.82    88.7  888.28
   108.4  874.98   128.2  860.88   187.3  815.88     207  801.27   226.8  787.57
   246.5  775.57   256.3  770.28   266.2  765.52   276.1  761.39   325.2  744.74
   354.6  734.13   374.3   726.2   376.6  725.71   384.1   724.1   391.6  724.52
   413.5  727.29   482.2   728.7     492  730.05   501.8  734.25   531.4  753.74
     561  772.39   669.4  837.05   679.3  841.93     699  850.17   817.3  908.83
#Mann= 3 , 0 , 0
       0      .1       0   376.6    .045       0   391.6      .1       0
Bank Sta=376.6,391.6
XS Rating Curve= 0 ,0
Exp/Cntr=0.3,0.1

Type RM Length L Ch R = 1 ,538.1   ,517.3,538.1,558.9
XS GIS Cut Line= 3
     1595748.263       372747.85     1596046.993       372879.79
     1596567.282       373093.88
#Sta/Elev= 30
     9.9  917.25    19.8  912.87    39.6  902.62   118.8  858.42   158.3  836.04
   237.5  789.84   267.2  773.14   306.8  752.56   346.7  734.39   356.7  730.73
   366.8  728.71   447.1  725.92   489.9  721.44   497.4  721.13   504.9   722.4
   507.4  722.82   517.5  727.04   537.6  738.28   547.6  744.66   597.8  779.83
     638  807.15   658.1  820.37   668.2  826.07   678.2  830.74   758.6  865.02
   808.8  890.02     859  917.96   869.1  923.09   879.1  927.61   889.2  931.05
#Mann= 3 , 0 , 0
       0     .08       0   489.9    .045       0   504.9     .08       0
Bank Sta=489.9,504.9
XS Rating Curve= 0 ,0
Exp/Cntr=0.3,0.1

Chan Stop Cuts=-1
Use User Specified Reach Order=0